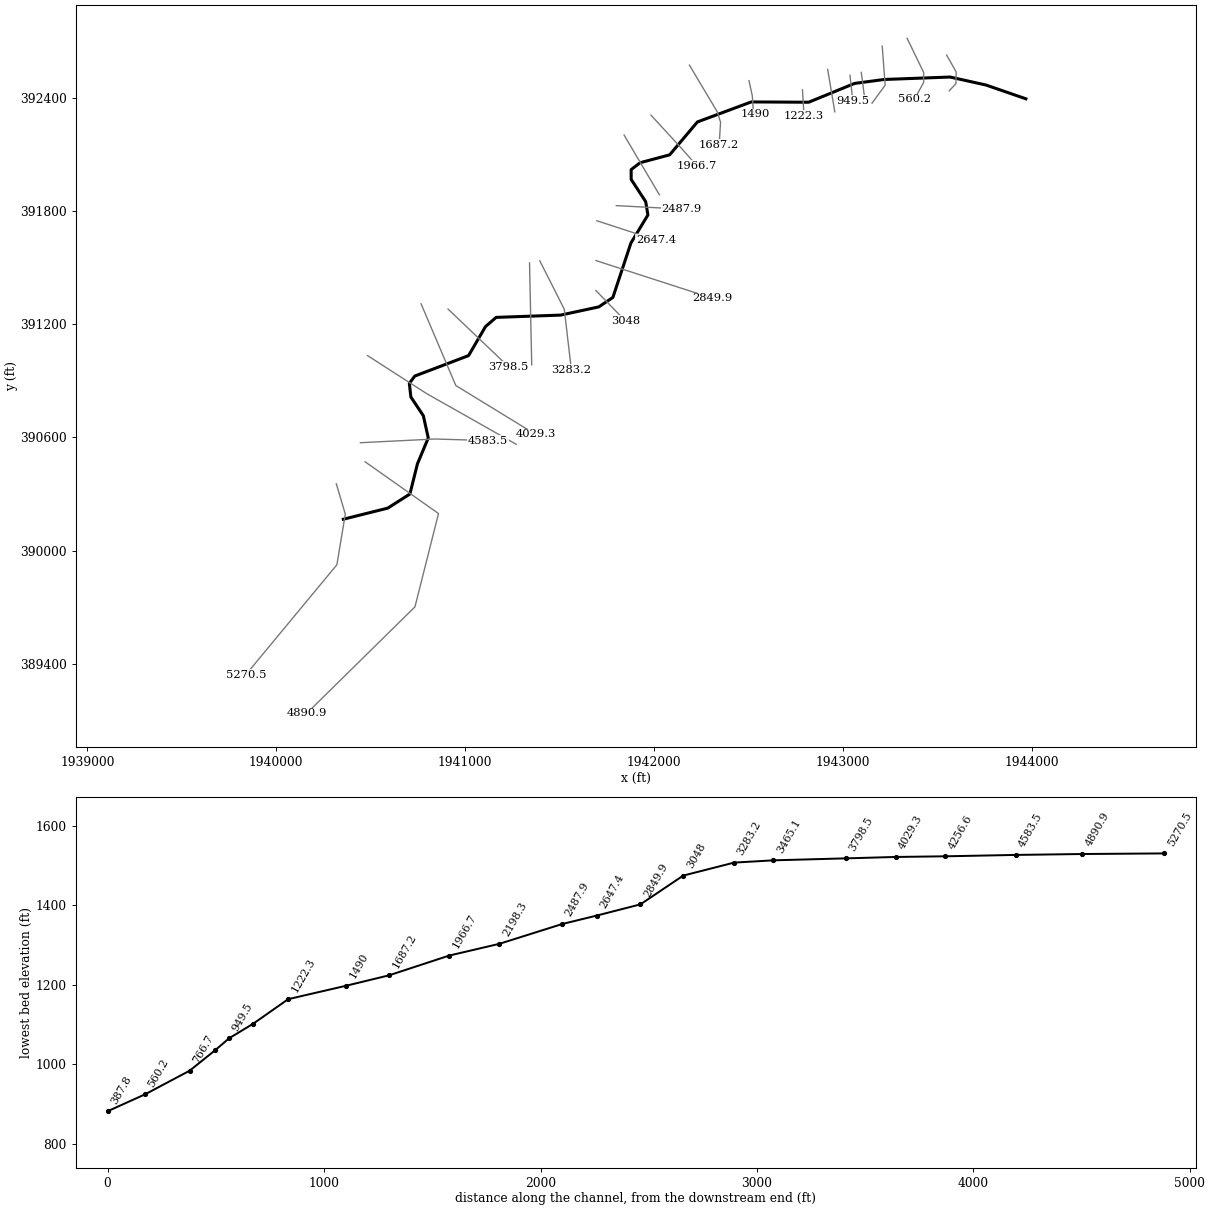
--- MarrBrnch.prj (project) ---

Proj Title=MarrBrnch
Current Plan=p01
Default Exp/Contr=0,0
English Units
Geom File=g01
Flow File=f01
Plan File=p01
BEGIN DESCRIPTION:
END DESCRIPTION:
DSS Export Rating Curves= 0
DSS Export Rating Curve Sorted= 0
DSS Export Volume Flow Curves= 0
DXF OffsetX= 0
DXF OffsetY= 0
DXF ScaleX= 0
DXF ScaleY= 0

--- MarrBrnch.p01 (plan) ---

Plan Title=Floodplain
Program Version=4.00
Geom File=g01
Flow File=f01
K Sum by GR=0
Std Step Tol=0.01
Critical Tol=0.01
Num of Std Step Trials=20
Max Error Tol=0.3
Flow Tol Ratio=0.001
Split Flow NTrial=30
Split Flow Tol=0.02
Split Flow Ratio=0.02
Log Output Level=0
Friction Slope Method=1
Unsteady Friction Slope Method=2
Unsteady Bridges Friction Slope Method=1
Global Log Level=0
CheckData=False
Run HTab=0
Run UNet=0
Run PostProcess=0
UNET Theta=0
UNET Theta Warmup=0
UNET ZTol=0
UNET ZSATol=0
UNET MxIter=0
UNET MaxInSteps=0
UNET DtIC=0
UNET DtMin=0
UNET MaxCRTS=0
UNET WFStab=0
UNET SFStab=0
UNET WFX=0
UNET SFX=0
UNET DSS MLevel=0
UNET DZMax Abort=0
UNET Convert EG Bridges=0
UNET Use Existing IB Tables=0
UNET Froude Limit=0
UNET Froude Power=0
Write IC File=0
Echo Input=False
Echo Output=False
Write Detailed=0

--- MarrBrnch.f01 (steady flow) ---

Flow Title=NFF Regression Equation
Program Version=4.00
Number of Profiles=1
Profile Names=P100yr
River Rch & RM=MarrBrnch,Main      ,5270.5
436.7353
River Rch & RM=MarrBrnch,Main      ,4890.9
712.4185
Boundary for River Rch & Prof#=MarrBrnch,Main      ,1
Up Type=0
Dn Type=3
Dn Slope=0.324047

--- MarrBrnch.g01 (geometry) ---

Geom Title=USGS 3m DEM
Program Version=4.10

River Reach=MarrBrnch       ,Main
Reach XY= 30
     1940355.131      390165.929     1940590.374      390224.818
     1940707.613      390299.528     1940747.492      390459.332
     1940804.783      390596.485     1940778.742       390714.54
     1940712.769      390813.499     1940704.622      390885.939
     1940733.603       390924.61     1941018.025      391032.742
     1941107.721      391186.417     1941164.158      391235.374
     1941506.172      391247.527     1941707.561      391290.929
     1941782.214      391341.277       1941877.7      391629.471
       1941967.6      391777.911      1941955.84       391848.57
     1941878.986      391966.341     1941878.778      392018.121
     1941926.311      392054.818     1942082.561      392096.485
     1942229.842      392270.954     1942514.553      392376.842
     1942818.689      392375.285     1943061.728      392474.957
     1943217.978      392495.791     1943566.996      392508.755
     1943757.908      392466.277     1943968.589       392393.36

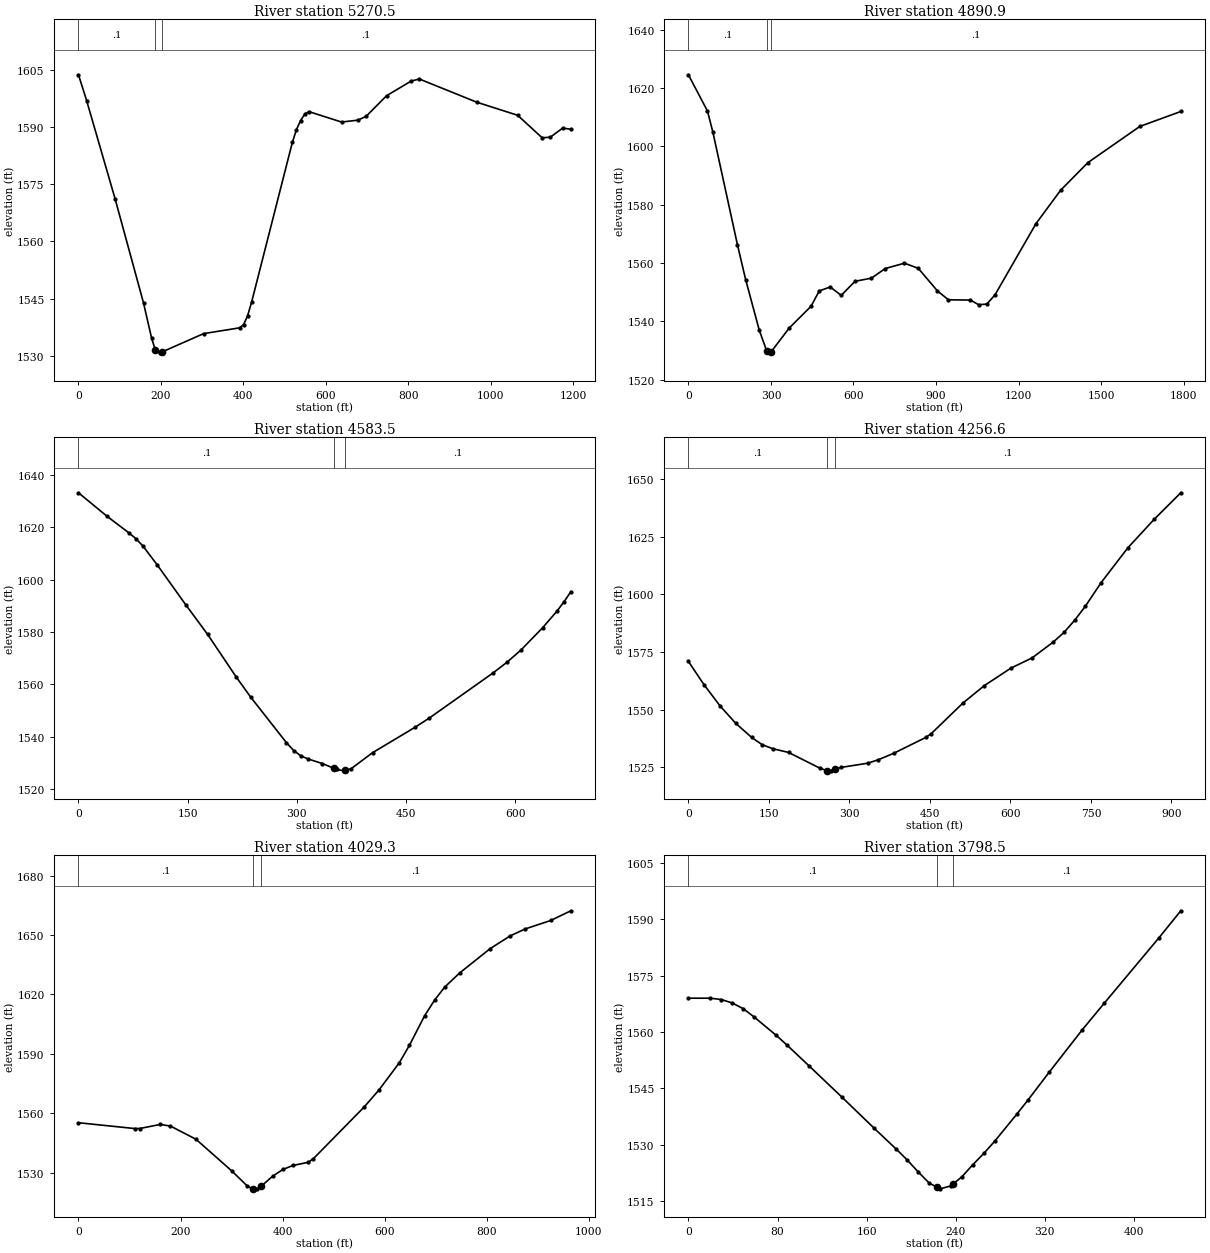
Type RM Length L Ch R = 1 ,5270.5  ,353.7,379.6,405.4
XS GIS Cut Line= 4
     1940318.051      390353.765     1940365.628      390192.985
     1940321.171      389924.894     1939839.722      389343.058
#Sta/Elev= 30
       0  1603.8    19.7 1597.04    88.8 1571.22   157.8 1543.84   177.4  1534.6
   186.6 1531.39   196.8 1530.72   201.6  1530.9   303.6 1535.77   390.9 1537.29
   400.6 1538.15   410.3 1540.46     420 1544.03   518.9 1586.03   528.9  1589.4
   538.8 1591.75   548.7 1593.39   558.7 1594.13   638.2 1591.38   677.9 1591.87
   697.8 1592.87   747.5  1598.3   807.1 1602.14     827 1602.69   966.1  1596.6
  1065.4 1593.16  1125.1 1587.23  1144.9 1587.41  1174.8 1589.79  1194.6 1589.48
#Mann= 3 , 0 , 0
       0      .1       0   186.6    .045       0   201.6      .1       0
Bank Sta=186.6,201.6
XS Rating Curve= 0 ,0
Exp/Cntr=0.3,0.1

Type RM Length L Ch R = 1 ,4890.9  ,292,307.2,322.4
XS GIS Cut Line= 4
     1940470.627      390470.248     1940859.087      390196.175
     1940734.401      389701.805     1940161.282      389137.435
#Sta/Elev= 30
       0 1624.53    69.3  1612.1    89.1 1604.78   178.3 1566.22     208 1554.31
   257.5 1536.97     284 1529.98   297.1 1529.19     299 1529.33   366.5 1537.71
   445.7 1545.16   475.4  1550.4   515.4 1551.78   555.4 1548.88   605.4 1553.72
   665.4  1554.8   715.3  1558.1   785.3 1559.93   835.3 1558.17   905.3  1550.4
   945.3 1547.37    1025 1547.29  1054.8 1545.69  1084.6  1545.9  1114.4 1549.09
  1263.3  1573.5  1352.7 1584.92    1452 1594.42  1640.7 1606.82  1789.6 1611.94
#Mann= 3 , 0 , 0
       0      .1       0     284    .045       0     299      .1       0
Bank Sta=284,299
XS Rating Curve= 0 ,0
Exp/Cntr=0.3,0.1

Type RM Length L Ch R = 1 ,4583.5  ,341.1,326.9,312.5
XS GIS Cut Line= 3
      1940445.38      390571.327     1940839.126      390591.015
     1941121.311      390582.812
#Sta/Elev= 30
       0  1633.2    39.4 1624.18      69 1617.94    78.8  1615.7    88.7  1612.8
   108.4 1605.55   147.8 1590.23   177.4 1579.07   216.8 1562.74   236.5 1555.11
   285.8 1537.63   295.7 1534.65   305.5 1532.62   315.4 1531.44   335.1 1529.67
   351.6 1527.79   354.8 1527.41   364.7 1526.89   366.6 1527.04   374.5 1527.68
     404 1533.82   462.4 1543.54   481.8 1547.03   569.5  1564.3   588.9 1568.44
   608.4  1573.2   637.6 1581.57   657.1 1587.84   666.8 1591.41   676.5 1595.39
#Mann= 3 , 0 , 0
       0      .1       0   351.6    .045       0   366.6      .1       0
Bank Sta=351.6,366.6
XS Rating Curve= 0 ,0
Exp/Cntr=0.3,0.1

Type RM Length L Ch R = 1 ,4256.6  ,240.6,227.1,213.7
XS GIS Cut Line= 3
     1940483.137      391032.977     1940796.904      390831.182
     1941270.629      390562.942
#Sta/Elev= 30
       0 1570.87    29.4 1560.68    58.9  1551.6    88.4 1543.98   117.8 1537.92
   137.4 1534.77   157.1 1533.02   186.5 1531.41   245.4 1524.53   258.3 1523.51
   265.1 1523.42   273.3 1524.05   284.7 1524.92   333.8 1526.72   353.4 1528.19
     383 1531.08   442.3 1537.92   452.2  1539.5   511.6 1552.85   551.2 1560.36
   600.7 1567.95   640.3  1572.4   679.9  1579.3   699.7 1583.44   719.5 1588.68
   739.3 1594.72     769 1605.07   818.5 1620.09     868 1632.57   917.4 1644.03
#Mann= 3 , 0 , 0
       0      .1       0   258.3    .045       0   273.3      .1       0
Bank Sta=258.3,273.3
XS Rating Curve= 0 ,0
Exp/Cntr=0.3,0.1

Type RM Length L Ch R = 1 ,4029.3  ,221.9,231,240.2
XS GIS Cut Line= 3
     1940766.757      391307.368     1940950.711      390874.248
       1941372.4      390615.949
#Sta/Elev= 30
       0 1555.17   110.1 1552.24   120.1 1552.25   160.2  1554.3   180.2  1553.5
   230.3 1546.82   300.4 1530.85   330.4 1523.34   340.4 1521.78   342.7 1521.78
   350.4 1521.78   357.7 1523.01   380.5 1528.14   400.5 1531.55   420.5 1533.59
   450.5 1535.19   460.6 1537.06   559.6 1563.01   589.2 1571.78   628.8 1585.44
   648.6 1594.24   678.3 1609.13     698  1617.1   717.8 1623.68   747.5  1630.9
   806.8 1643.08   846.4 1649.59   876.1  1653.1   925.5 1657.32   965.1 1662.23
#Mann= 3 , 0 , 0
       0      .1       0   342.7    .045       0   357.7      .1       0
Bank Sta=342.7,357.7
XS Rating Curve= 0 ,0
Exp/Cntr=0.3,0.1

Type RM Length L Ch R = 1 ,3798.5  ,351.1,333.4,315.5
XS GIS Cut Line= 2
      1940909.49      391279.478     1941229.409      390974.325
#Sta/Elev= 30
       0 1568.99    19.6 1568.99    29.5 1568.64    39.3 1567.72    49.1 1566.22
      59 1563.99    78.6 1559.16    88.4 1556.54   108.1 1551.04   137.6 1542.72
     167 1534.31   186.7 1528.79   196.5 1525.92   206.3 1522.75   216.2 1519.78
   222.8 1518.74     226 1518.24   235.8 1519.04   237.8 1519.54   245.6 1521.47
   255.4 1524.68   265.3 1527.69   275.1 1530.95   294.7 1538.07   304.6 1541.77
   324.2 1549.39   353.7  1560.6   373.3 1567.63   422.5 1585.07   442.1 1592.26
#Mann= 3 , 0 , 0
       0      .1       0   222.8    .045       0   237.8      .1       0
Bank Sta=222.8,237.8
XS Rating Curve= 0 ,0
Exp/Cntr=0.3,0.1

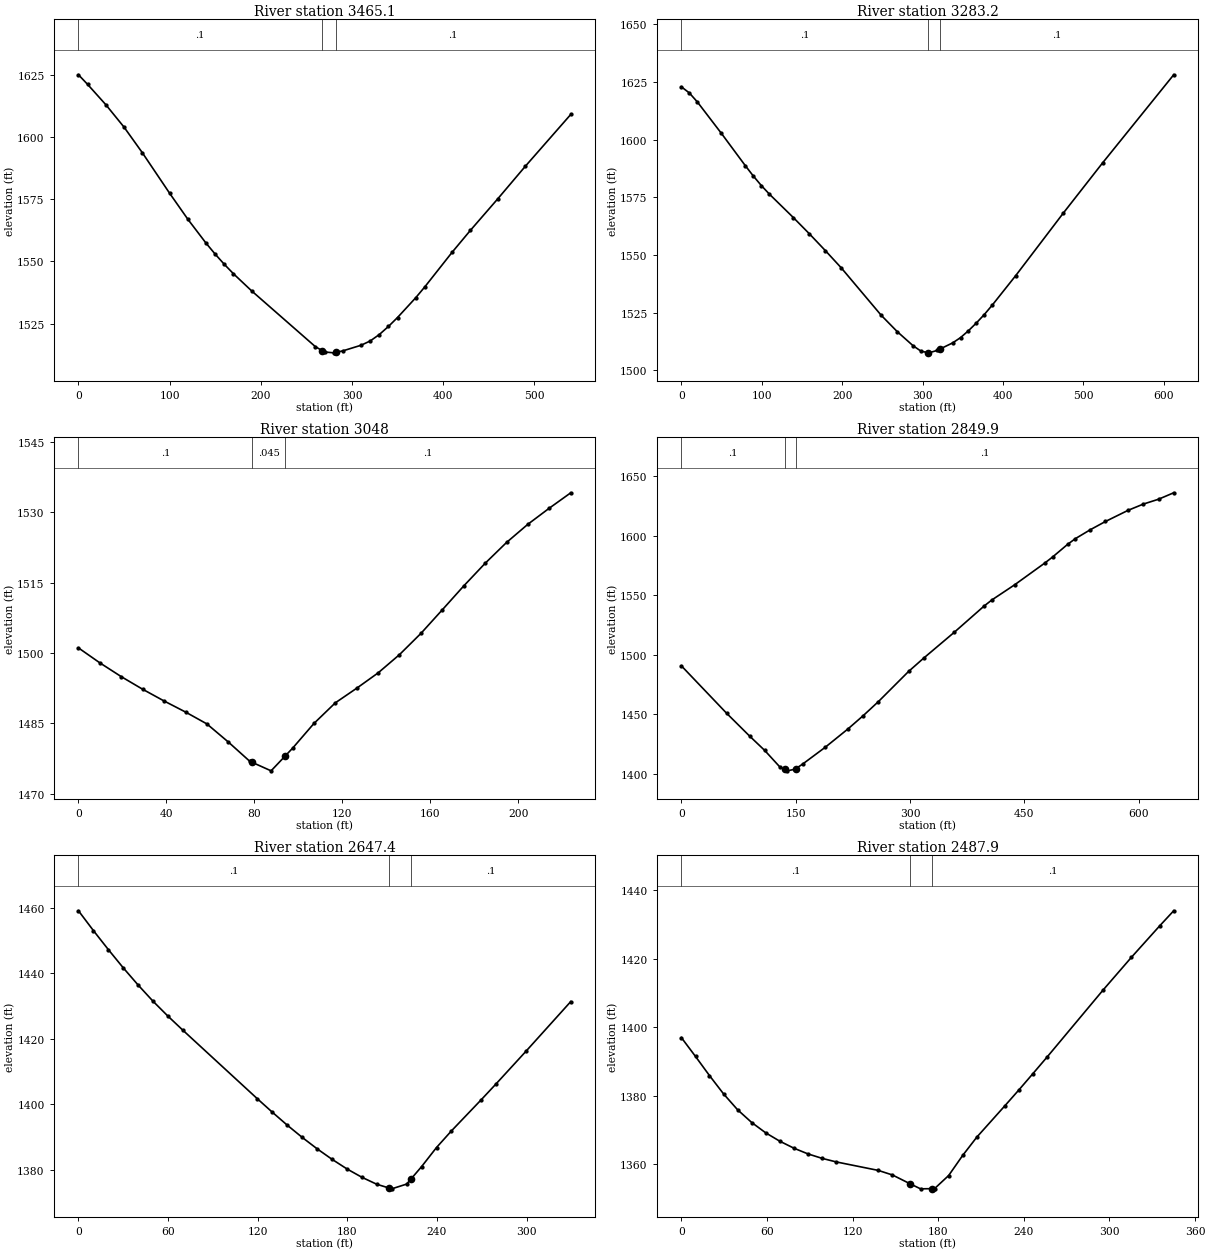
Type RM Length L Ch R = 1 ,3465.1  ,179.7,181.8,184
XS GIS Cut Line= 2
      1941340.97      391523.929     1941352.455      390984.168
#Sta/Elev= 30
       0    1625      10 1621.15      30 1612.98      50 1603.96      70 1593.71
     100 1577.39     120 1566.94     140 1557.32     150 1552.92     160 1548.84
     170 1545.06     190 1538.16   259.9 1515.75   267.2 1514.22   269.9 1513.65
   279.9  1513.3   282.2 1513.48   289.9 1514.09   309.9 1516.35   319.9 1518.06
   329.9 1520.64   339.9 1523.89   349.9 1527.49   369.9 1535.45   379.9 1539.84
   409.9 1553.76   429.9 1562.54   459.9  1575.2   489.9 1588.18   539.9 1609.07
#Mann= 3 , 0 , 0
       0      .1       0   267.2    .045       0   282.2      .1       0
Bank Sta=267.2,282.2
XS Rating Curve= 0 ,0
Exp/Cntr=0.3,0.1

Type RM Length L Ch R = 1 ,3283.2  ,220.3,235.2,250.1
XS GIS Cut Line= 3
     1941395.111      391535.413     1941525.094      391278.072
     1941562.453      390956.278
#Sta/Elev= 30
       0 1622.83     9.9 1620.18    19.9 1616.27    49.7  1602.7    79.5 1588.68
    89.5 1584.18    99.4 1580.08   109.4 1576.36   139.2 1566.21   159.1 1559.19
     179  1551.9   198.8 1544.42   248.5 1523.87   268.4  1516.8   288.3 1510.63
   298.1  1508.3   306.2 1507.71   307.9 1507.59   317.8 1508.61   321.2 1509.17
   337.4  1511.9   347.2 1514.19     357 1517.16   366.8  1520.5   376.7 1524.17
   386.5  1528.2   415.9 1541.08   474.8 1568.04   523.9 1589.89   612.3 1628.05
#Mann= 3 , 0 , 0
       0      .1       0   306.2    .045       0   321.2      .1       0
Bank Sta=306.2,321.2
XS Rating Curve= 0 ,0
Exp/Cntr=0.3,0.1

Type RM Length L Ch R = 1 ,3048    ,187,198,209
XS GIS Cut Line= 2
     1941692.061      391377.915     1941847.919      391217.135
#Sta/Elev= 26
       0 1501.08     9.7  1497.9    19.5 1494.94    29.2 1492.26    38.9 1489.77
    48.7  1487.4    58.4 1484.87    68.2 1480.99    77.9  1476.9      79 1476.67
    87.6 1474.86      94 1478.02    97.4  1479.7   107.1 1484.97   116.8 1489.36
   126.6  1492.5   136.3 1495.76     146 1499.65   155.8  1504.2   165.5 1509.22
   175.2 1514.29     185 1519.15   194.7 1523.58   204.4 1527.46   214.2 1530.91
   223.9 1534.17
#Mann= 3 , 0 , 0
       0      .1       0      79    .045       0      94      .1       0
Bank Sta=79,94
XS Rating Curve= 0 ,0
Exp/Cntr=0.3,0.1

Type RM Length L Ch R = 1 ,2849.9  ,202.6,202.5,202.6
XS GIS Cut Line= 2
     1941692.731      391536.253     1942307.289       391337.31
#Sta/Elev= 30
       0 1490.62    59.6 1450.63    89.4 1431.69   109.3 1419.58   129.2 1405.67
   135.4 1403.63   139.1 1402.41   149.1  1403.8   150.4 1404.36     159 1408.04
   188.8 1422.23   218.6 1437.63   238.5 1448.72   258.4  1460.5   298.1  1485.9
     318 1497.14   357.8 1518.66   397.5 1541.01   407.4 1545.97   437.3 1558.71
     477 1577.05     487 1582.02   506.8 1592.69   516.8 1597.41   536.6 1604.99
   556.5 1611.92   586.3 1621.32   606.2 1626.53   626.1  1630.6     646 1636.02
#Mann= 3 , 0 , 0
       0      .1       0   135.4    .045       0   150.4      .1       0
Bank Sta=135.4,150.4
XS Rating Curve= 0 ,0
Exp/Cntr=0.3,0.1

Type RM Length L Ch R = 1 ,2647.4  ,154.4,159.6,165.2
XS GIS Cut Line= 2
     1941696.962      391747.399     1942010.339      391645.334
#Sta/Elev= 28
       0 1459.05      10    1453      20  1447.2      30 1441.61      40 1436.34
    49.9 1431.43    59.9 1426.87    69.9 1422.57   119.8 1401.62   129.8 1397.52
   139.8 1393.56   149.8 1389.83   159.8 1386.34   169.8 1383.13   179.8 1380.19
   189.8 1377.64   199.7 1375.52   207.8 1374.39   209.7 1374.12   219.7 1375.57
   222.8 1377.22   229.7  1380.9   239.7 1386.74   249.7 1391.82   269.7 1401.36
   279.6 1406.19   299.6 1416.14   329.6 1431.32
#Mann= 3 , 0 , 0
       0      .1       0   207.8    .045       0   222.8      .1       0
Bank Sta=207.8,222.8
XS Rating Curve= 0 ,0
Exp/Cntr=0.3,0.1

Type RM Length L Ch R = 1 ,2487.9  ,310.9,289,266.8
XS GIS Cut Line= 2
     1941800.341      391827.441     1942144.869      391809.395
#Sta/Elev= 29
       0 1397.02     9.9 1391.52    19.7 1385.93    29.6 1380.57    39.4 1375.95
    49.3 1372.23    59.1 1369.22      69 1366.77    78.9 1364.73    88.7 1363.07
    98.6 1361.77   108.4 1360.74     138 1358.25   147.9 1356.92   160.5  1354.3
   167.6 1352.87   175.5 1352.92   177.4 1352.93   187.3 1356.76   197.1 1362.61
     207 1367.95   226.7 1377.12   236.6 1381.79   246.4 1386.53   256.3 1391.36
   295.7    1411   315.4 1420.48   335.1 1429.61     345 1434.05
#Mann= 3 , 0 , 0
       0      .1       0   160.5    .045       0   175.5      .1       0
Bank Sta=160.5,175.5
XS Rating Curve= 0 ,0
Exp/Cntr=0.3,0.1

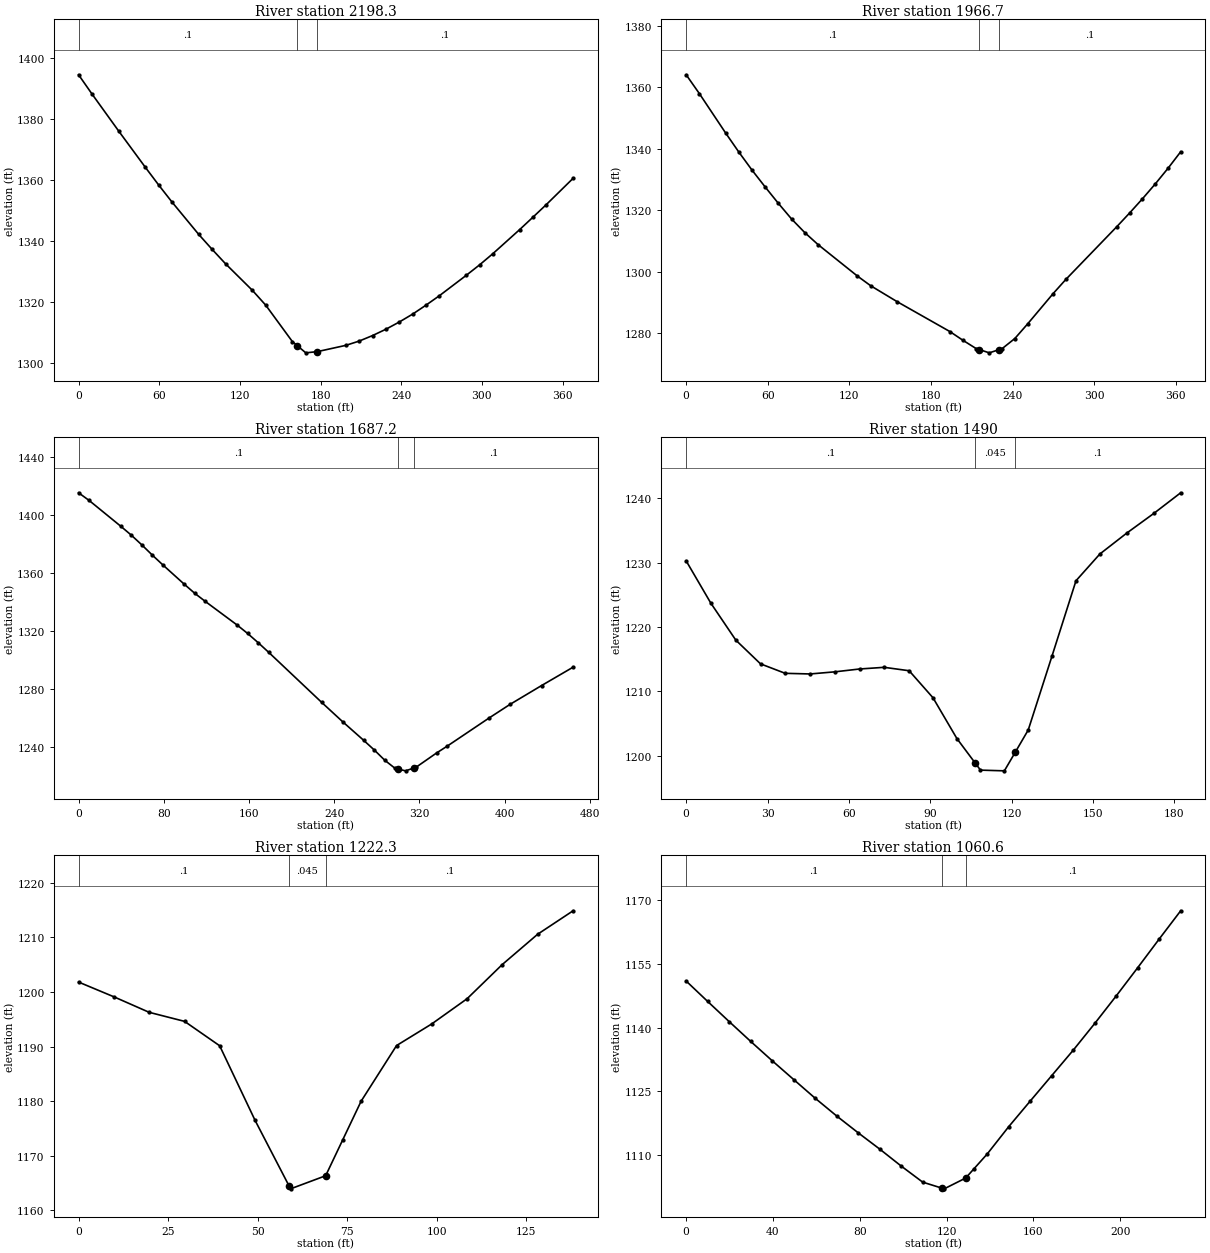
Type RM Length L Ch R = 1 ,2198.3  ,226.9,231.5,235.6
XS GIS Cut Line= 2
     1941841.356        392201.5     1942028.386      391884.863
#Sta/Elev= 30
       0 1394.45     9.9 1388.19    29.8    1376    49.7 1364.06    59.6 1358.26
    69.6 1352.62    89.4 1342.04    99.4 1337.12   109.3 1332.43   129.2 1323.74
   139.2 1318.84     159  1306.9   162.6 1305.57     169  1303.2   177.6  1303.6
   198.8 1305.66   208.7 1307.06   218.7 1308.88   228.6 1310.95   238.5 1313.31
   248.5 1315.92   258.4 1318.85   268.4 1321.96   288.2 1328.59   298.2 1332.05
   308.1 1335.73     328 1343.62   337.9  1347.7   347.9 1351.86   367.8 1360.47
#Mann= 3 , 0 , 0
       0      .1       0   162.6    .045       0   177.6      .1       0
Bank Sta=162.6,177.6
XS Rating Curve= 0 ,0
Exp/Cntr=0.3,0.1

Type RM Length L Ch R = 1 ,1966.7  ,288.5,279.3,269.7
XS GIS Cut Line= 3
     1941984.089      392306.499     1942134.877      392142.462
      1942228.54      392037.439
#Sta/Elev= 30
       0 1364.07     9.7 1357.95    29.1 1345.08    38.8 1338.89    48.4 1333.08
    58.1 1327.58    67.8 1322.25    77.5 1317.18    87.2 1312.76    96.9 1308.88
   125.9 1298.63   135.6  1295.5     155 1290.33   193.8 1280.61   203.4 1277.77
   213.1 1275.08   215.3 1274.76   222.8 1273.68   230.3 1274.76   232.2 1275.03
   241.6 1278.34     251 1283.09   269.7 1292.92   279.1 1297.55   316.6 1314.72
     326 1319.16   335.4 1323.76   344.8 1328.58   354.2 1333.68   363.5 1339.04
#Mann= 3 , 0 , 0
       0      .1       0   215.3    .045       0   230.3      .1       0
Bank Sta=215.3,230.3
XS Rating Curve= 0 ,0
Exp/Cntr=0.3,0.1

Type RM Length L Ch R = 1 ,1687.2  ,203.5,197.2,191.7
XS GIS Cut Line= 4
      1942187.32      392571.868     1942334.506      392324.788
     1942352.201      392269.175     1942344.818      392151.052
#Sta/Elev= 30
       0 1415.05     9.9 1409.77    39.7 1391.97    49.6 1385.84    59.5 1379.12
    69.4 1372.06    79.3 1365.31    99.2 1352.17   109.1 1345.88     119  1340.3
   148.8  1324.1   158.7 1318.28   168.6 1311.94   178.5  1305.3   228.1 1270.96
   247.9 1257.59   267.8 1244.68   277.7 1238.06   287.6 1230.98   297.3 1225.41
   300.3  1224.9     307 1223.77   315.3 1225.84   316.8 1226.21   336.2  1236.1
     346 1240.71   385.4 1260.11   405.1 1269.49   434.7 1282.44   464.3 1295.08
#Mann= 3 , 0 , 0
       0      .1       0   300.3    .045       0   315.3      .1       0
Bank Sta=300.3,315.3
XS Rating Curve= 0 ,0
Exp/Cntr=0.3,0.1

Type RM Length L Ch R = 1 ,1490    ,267.9,267.7,267.6
XS GIS Cut Line= 4
     1942502.755      392489.404     1942520.289      392409.117
     1942524.903      392338.981     1942535.977      392311.296
#Sta/Elev= 23
       0 1230.25     9.1 1223.69    18.3 1217.96    27.4 1214.28    36.5 1212.81
    45.7 1212.71    54.8 1213.04    63.9 1213.48      73 1213.74    82.2 1213.21
      91 1209.01    99.8 1202.69   106.4 1198.97   108.5 1197.79   117.3 1197.68
   121.4 1200.63   126.1 1204.02   134.9 1215.54   143.7 1227.17   152.5 1231.32
   162.4 1234.56   172.4 1237.62   182.3 1240.82
#Mann= 3 , 0 , 0
       0      .1       0   106.4    .045       0   121.4      .1       0
Bank Sta=106.4,121.4
XS Rating Curve= 0 ,0
Exp/Cntr=0.3,0.1

Type RM Length L Ch R = 1 ,1222.3  ,160,161.7,163.3
XS GIS Cut Line= 2
     1942785.834      392440.619     1942794.037      392302.808
#Sta/Elev= 17
       0 1201.83     9.9 1199.12    19.7 1196.29    29.6 1194.63    39.4 1190.16
    49.3 1176.48    58.8 1164.46    59.2 1163.95      69 1166.35    73.8 1172.97
    78.9    1180    88.8  1190.2    98.6 1194.15   108.5 1198.78   118.3 1205.03
   128.2 1210.59   138.1 1214.89
#Mann= 3 , 0 , 0
       0      .1       0    58.8    .045       0      69      .1       0
Bank Sta=58.8,69
XS Rating Curve= 0 ,0
Exp/Cntr=0.3,0.1

Type RM Length L Ch R = 1 ,1060.6  ,112.4,111.1,110
XS GIS Cut Line= 2
     1942919.236      392549.309      1942956.97      392324.546
#Sta/Elev= 26
       0  1150.9     9.9 1146.12    19.8  1141.4    29.7 1136.76    39.6 1132.23
    49.6 1127.78    59.4 1123.44    69.4 1119.24    79.3  1115.3    89.2 1111.49
    99.1 1107.51     109 1103.74   117.7 1102.36   118.9 1102.17   128.8  1104.7
   132.7 1106.91   138.7 1110.32   148.6 1116.72   158.6 1122.78   168.4 1128.68
   178.4  1134.7   188.3 1140.96   198.2 1147.42   208.1 1154.04     218 1160.76
   227.9 1167.38
#Mann= 3 , 0 , 0
       0      .1       0   117.7    .045       0   128.8      .1       0
Bank Sta=117.7,128.8
XS Rating Curve= 0 ,0
Exp/Cntr=0.3,0.1

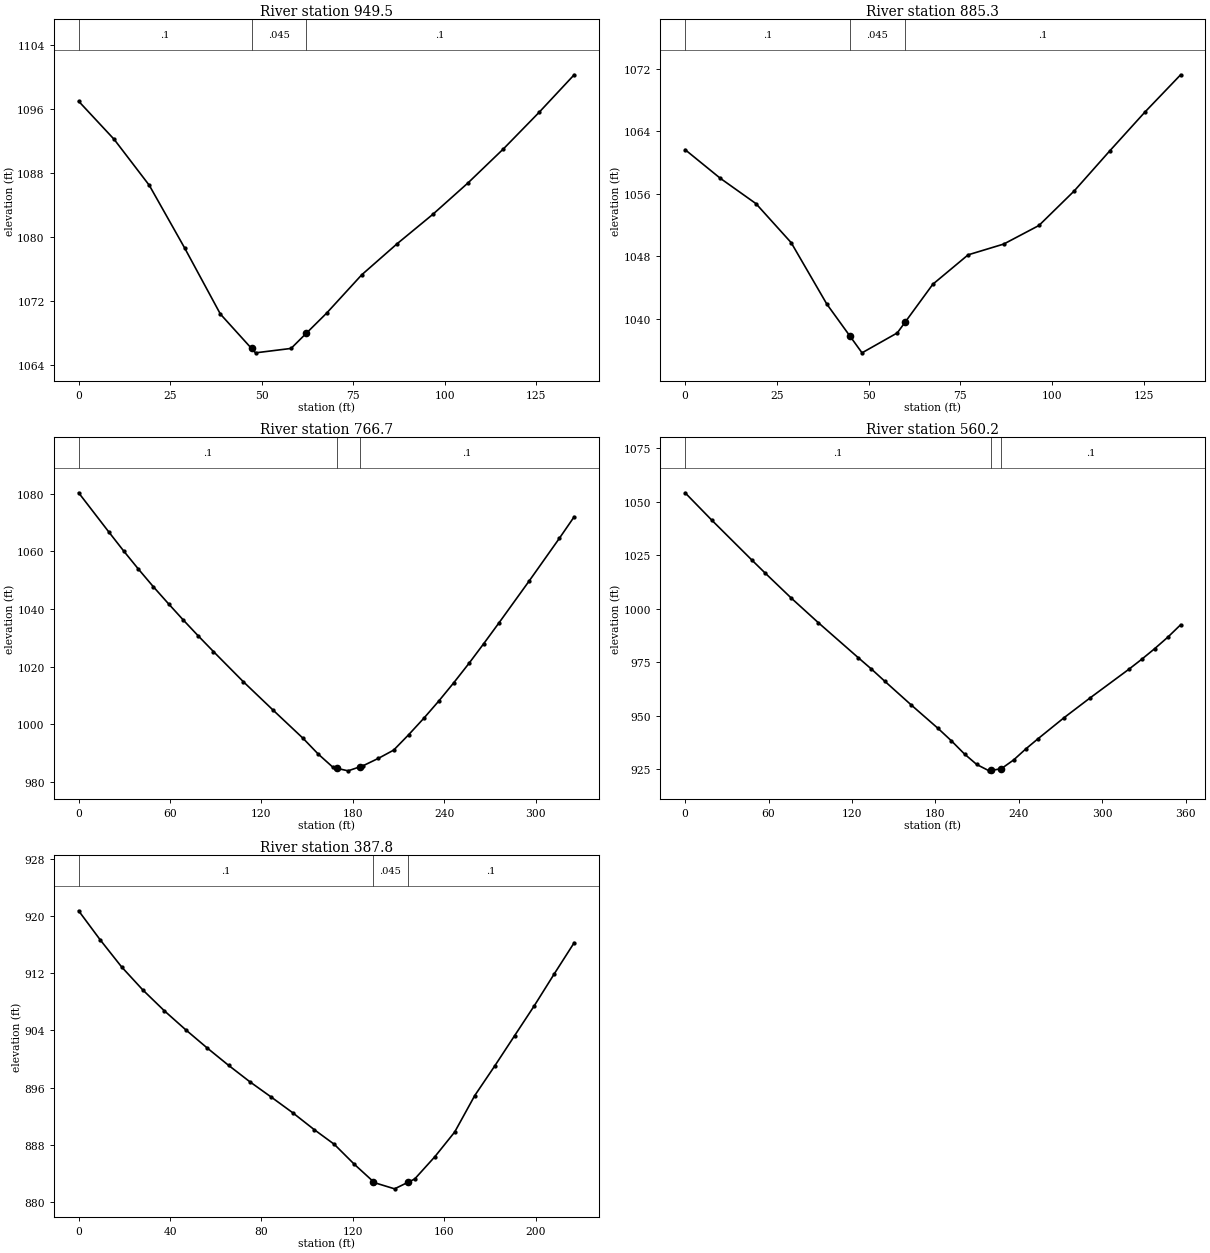
Type RM Length L Ch R = 1 ,949.5   ,63.2,64.2,65.3
XS GIS Cut Line= 2
      1943037.36      392518.138     1943052.126      392383.608
#Sta/Elev= 17
       0 1096.94     9.7 1092.18    19.3 1086.44      29 1078.58    38.7 1070.38
    47.2 1066.09    48.3 1065.54      58 1066.09    62.2    1068    67.7 1070.49
    77.3 1075.28      87 1079.17    96.7 1082.82   106.3 1086.74     116    1091
   125.7 1095.54   135.3 1100.24
#Mann= 3 , 0 , 0
       0      .1       0    47.2    .045       0    62.2      .1       0
Bank Sta=47.2,62.2
XS Rating Curve= 0 ,0
Exp/Cntr=0.3,0.1

Type RM Length L Ch R = 1 ,885.3   ,119.8,118.6,117.7
XS GIS Cut Line= 2
     1943097.066      392533.701       1943114.6      392399.889
#Sta/Elev= 17
       0 1061.63     9.6 1057.96    19.3 1054.72    28.9 1049.72    38.6 1041.86
    44.9 1037.76    48.2 1035.61    57.8 1038.16    59.9 1039.51    67.5  1044.4
    77.1 1048.16    86.8 1049.54    96.4 1051.92     106 1056.34   115.7 1061.48
   125.3 1066.46     135 1071.22
#Mann= 3 , 0 , 0
       0      .1       0    44.9    .045       0    59.9      .1       0
Bank Sta=44.9,59.9
XS Rating Curve= 0 ,0
Exp/Cntr=0.3,0.1

Type RM Length L Ch R = 1 ,766.7   ,208.3,206.5,204.4
XS GIS Cut Line= 4
     1943207.983      392672.355     1943221.208      392495.931
     1943224.006       392466.21     1943154.048      392370.483
#Sta/Elev= 30
       0  1080.3    19.7 1066.78    29.5 1060.15    39.3 1053.78    49.1 1047.66
      59 1041.78    68.8 1036.09    78.6 1030.59    88.5  1025.2   108.1 1014.74
   127.8  1004.8   147.4  995.05   157.3  989.61   167.1  984.96   169.4  984.69
   176.9   983.8   184.4  985.16   186.9  985.61   196.8  988.14   206.8  990.99
   216.6  996.31   226.5 1001.99   236.4 1008.01   246.3  1014.4   256.2 1021.07
     266 1027.99   275.9 1035.13   295.7 1049.65   315.5 1064.44   325.3 1071.97
#Mann= 3 , 0 , 0
       0      .1       0   169.4    .045       0   184.4      .1       0
Bank Sta=169.4,184.4
XS Rating Curve= 0 ,0
Exp/Cntr=0.3,0.1

Type RM Length L Ch R = 1 ,560.2   ,172.8,172.3,171.9
XS GIS Cut Line= 4
     1943339.847       392713.78     1943427.336      392532.903
      1943427.21      392479.994     1943377.991       392390.17
#Sta/Elev= 27
       0 1054.27    19.1 1041.52    47.8 1022.94    57.4 1016.82    76.5 1004.91
    95.7  993.56   124.4  977.19     134   971.8   143.5  966.16   162.6  955.01
   181.8   944.1   191.4  938.29   200.9  932.07   209.7  927.17   218.6   924.2
   220.1  924.37   227.4  925.22   236.2  929.28     245  934.47   253.8  939.24
   272.5  949.07   291.1  958.27     319  971.68   328.3  976.38   337.6  981.33
     347  986.68   356.3  992.53
#Mann= 3 , 0 , 0
       0      .1       0   220.1    .045       0   227.4      .1       0
Bank Sta=220.1,227.4
XS Rating Curve= 0 ,0
Exp/Cntr=0.3,0.1

Type RM Length L Ch R = 1 ,387.8   ,392.5,387.7,383
XS GIS Cut Line= 4
     1943549.025      392625.188     1943599.652       392535.36
     1943598.243      392473.841      1943562.56      392435.697
#Sta/Elev= 27
       0  920.75     9.4   916.7    18.8   912.9    28.1  909.67    37.5  906.76
    46.9  904.09    56.2  901.57    65.6  899.13      75  896.81    84.4  894.66
    93.7  892.49   103.1  890.13   111.9  888.07   120.7  885.27     129  882.85
   129.5   882.7   138.3  881.84     144  882.73   147.1  883.22   155.9  886.33
   164.6  889.79   173.4   894.9   182.1  899.02   190.8  903.26   199.5  907.49
   208.2  911.93   216.9  916.28
#Mann= 3 , 0 , 0
       0      .1       0     129    .045       0     144      .1       0
Bank Sta=129,144
XS Rating Curve= 0 ,0
Exp/Cntr=0.3,0.1

Chan Stop Cuts=-1
Use User Specified Reach Order=0
Composite Channel Slope=5